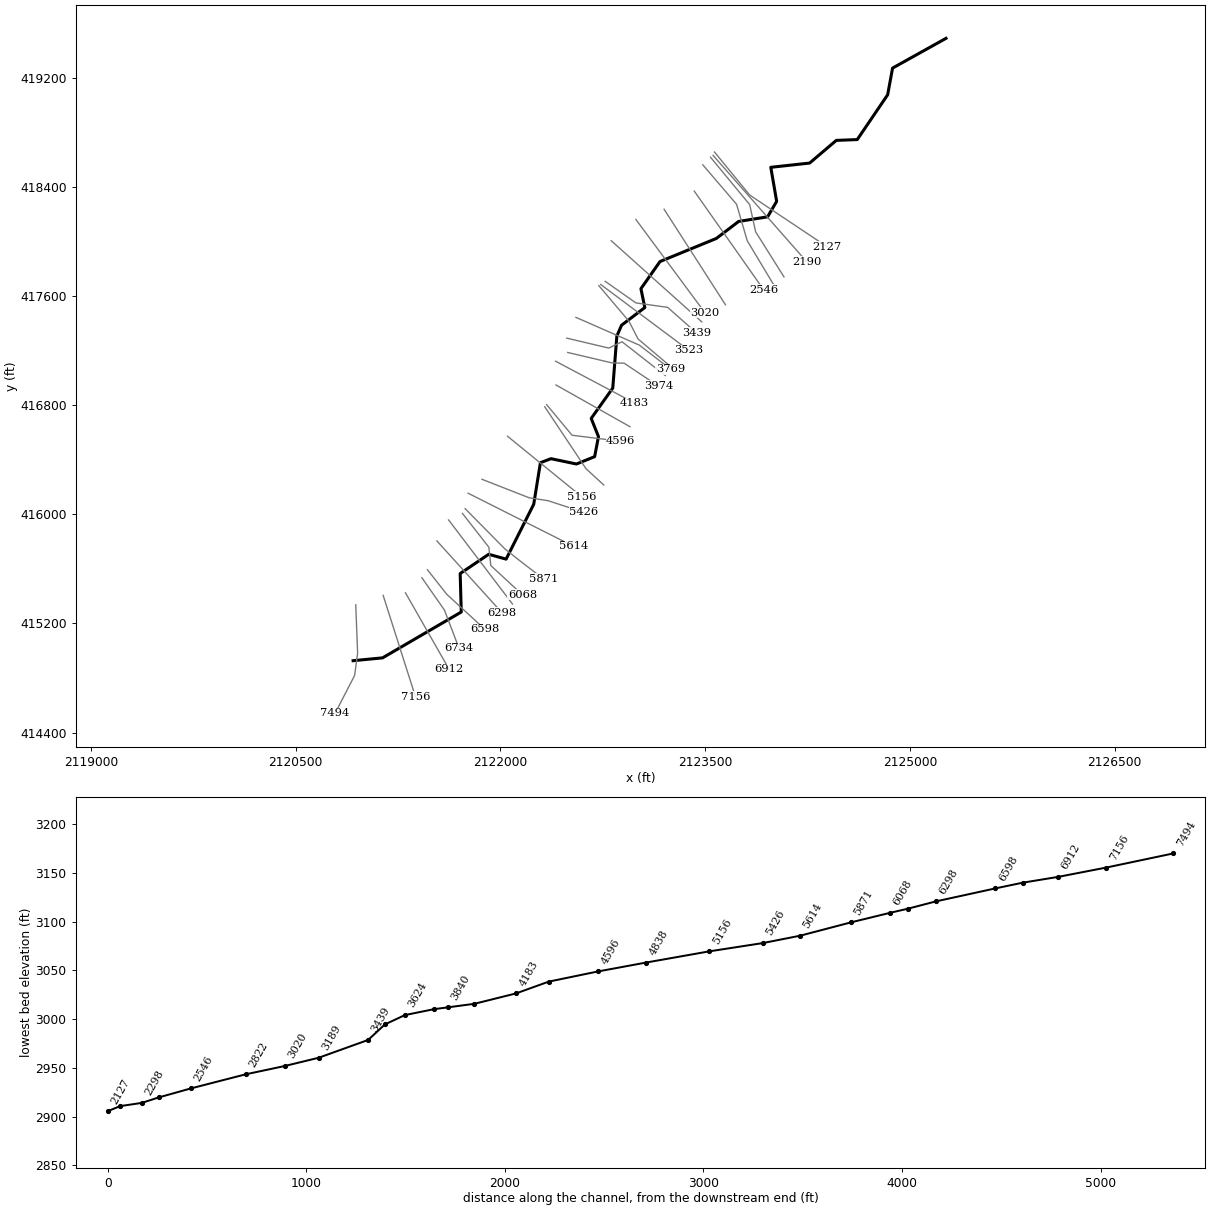
--- BECKYRN.prj (project) ---

Proj Title=BECKYRN
Current Plan=p01
Default Exp/Contr=0,0
English Units
Geom File=g01
Flow File=f01
Plan File=p01
BEGIN DESCRIPTION:
Stream Name- Becky Run
Flood Zone: Zone A
Greenbrier County, WV
County-Wide Study
WVDHSEM-2018-3, Flood Risk Project
HEC-RAS Version: 5.0.7
General Notes:
For the Hydrology Regression was used.
END DESCRIPTION:
DSS Export Rating Curves= 0
DSS Export Rating Curve Sorted= 0
DSS Export Volume Flow Curves= 0
DXF Filename=..\..\..\..\..\fz_Working\Nov1\Models\BECKYRN\BECKYRN.
DXF OffsetX= 0
DXF OffsetY= 0
DXF ScaleX= 0
DXF ScaleY= 0

--- BECKYRN.p01 (plan) ---

Plan Title=Floodplain
Program Version=5.07
Short Identifier=Floodplain
Geom File=g01
Flow File=f01
Subcritical Flow
K Sum by GR= 0
Std Step Tol= 0.01
Critical Tol= 0.01
Num of Std Step Trials= 20
Max Error Tol= 0.3
Flow Tol Ratio= 0.001
Split Flow NTrial= 30
Split Flow Tol= 0.02
Split Flow Ratio= 0.02
Log Output Level= 0
Friction Slope Method= 1
Unsteady Friction Slope Method= 2
Unsteady Bridges Friction Slope Method= 1
Parabolic Critical Depth
Global Vel Dist= 0 , 0 , 0
Global Log Level= 0
CheckData=False
Encroach Param=-1 ,0,0, 0
Mapping Interval=1HOUR
Computation Time Step Use Courant=        0
Computation Time Step Use Time Series=    0
Computation Time Step Count To Double=0
Computation Time Step Max Doubling=0
Computation Time Step Max Halving=0
Computation Time Step Residence Courant=0
Run HTab= 0
Run UNet= 0
Run Sediment= 0
Run PostProcess= 0
Run WQNet= 0
Run RASMapper= 0
UNET Theta= 0
UNET Theta Warmup= 0
UNET ZTol= 0
UNET ZSATol= 0
UNET MxIter= 0
UNET Max Iter WO Improvement= 0
UNET MaxInSteps= 0
UNET DtIC= 0
UNET DtMin= 0
UNET MaxCRTS= 0
UNET WFStab= 0
UNET SFStab= 0
UNET WFX= 1
UNET SFX= 1
UNET 1D Methodology=Finite Difference
UNET DSS MLevel= 1
UNET Pardiso=0
UNET DZMax Abort= 0
UNET Use Existing IB Tables= 0
UNET Froude Reduction=False
UNET Froude Limit= 0
UNET Froude Power= 0
UNET D1 Cores= 0
UNET D2 Coriolis=0
UNET D2 Cores= 0
UNET D2 Theta= 1
UNET D2 Theta Warmup= 1
UNET D2 Z Tol= 0.01
UNET D2 Volume Tol= 0.01
UNET D2 Max Iterations= 20
UNET D2 Equation= 0
UNET D2 RampUpFraction=0.1
UNET D2 TimeSlices= 1
UNET D2 BCVolumeCheck=0
UNET D1D2 MaxIter= 0
UNET D1D2 ZTol=0.01
UNET D1D2 QTol=0.1
UNET D1D2 MinQTol=1
Write IC File= 0
Write IC File at Fixed DateTime=0
Write IC File at Sim End=0
Echo Input=False
Echo Parameters=False
Echo Output=False
Write Detailed= 0
HDF Write Warmup=0
HDF Write Time Slices=0
HDF Flush=0
HDF Face Node Velocities=0
HDF Compression= 1
HDF Chunk Size= 1
HDF Spatial Parts= 1
HDF Use Max Rows=0
HDF Fixed Rows= 1
Calibration Method= 0
Calibration Iterations= 20
Calibration Max Change=0.05
Calibration Tolerance=0.2
Calibration Maximum=1.5
Calibration Minimum=0.5
Calibration Optimization Method= 1
WQ AD Non Conservative
WQ ULTIMATE=-1
WQ Max Comp Step=1HOUR
WQ Output Interval=15MIN
WQ Output Selected Increments= 0
WQ Output face flow=0
WQ Output face velocity=0
WQ Output face area=0
WQ Output face dispersion=0
WQ Output cell volume=0
WQ Output cell surface area=0
WQ Output cell continuity=0
WQ Output cumulative cell continuity=0
WQ Output face conc=0
WQ Output face dconc_dx=0
WQ Output face courant=0
WQ Output face peclet=0
WQ Output face adv mass=0
WQ Output face disp mass=0
WQ Output cell mass=0
WQ Output cell source sink temp=0
WQ Output nsm pathways=0
WQ Output nsm derived pathways=0
WQ Output MaxMinRange=-1
WQ Daily Max Min Mean=-1
WQ Daily Range=0
WQ Daily Time=0
WQ Create Restart=0
WQ Fixed Restart=0
WQ System Summary=0
WQ Write To DSS=0
WQ Use Fixed Temperature=0
Sorting and Armoring Iterations= 10
XS Update Threshold= 0.02
Bed Roughness Predictor= 0
Hydraulics Update Threshold= 0.02
Energy Slope Method= 1
Volume Change Method= 1
Sediment Retention Method= 0
XS Weighting Method= 0
Number of US Weighted Cross Sections= 1
Number of DS Weighted Cross Sections= 1
Upstream XS Weight=0
Main XS Weight=1
Downstream XS Weight=0
Number of DS XS's Weighted with US Boundary= 1
Upstream Boundary Weight= 1
Weight of XSs Associated with US Boundary= 0
Number of US XS's Weighted with DS Boundary= 1
Downstream Boundary Weight= 0.5
Weight of XSs Associated with DS Boundary= 0.5
Percentile Method= 0
Sediment Output Level= 3
Mass or Volume Output= 0
Output Increment Type= 1
Profile and TS Output Increment= 1
XS Output Flag= 0
XS Output Increment= 10
Write Gradation File= 0
Read Gradation Hotstart= 0
Write HDF5 File= 1
Write Binary Output= 1
Write DSS Sediment File= 0
SV Curve= 0
Specific Gage Flag= 0

--- BECKYRN.f01 (steady flow) ---

Flow Title=NFF Regression Equation
Program Version=5.07
Number of Profiles= 6
Profile Names=f1p,f10p,f4p,f2p,f02p,f1pplus
River Rch & RM=River 1,Reach 1         ,7494
     580     307     408     491     810     858
River Rch & RM=River 1,Reach 1         ,6298
     691     368     488     586     962    1020
River Rch & RM=River 1,Reach 1         ,3624
     770     412     544     654    1070    1140
River Rch & RM=BECKYRN,Main            ,7494
     580     307     408     491     810     858
River Rch & RM=BECKYRN,Main            ,6298
     691     368     488     586     962    1020
River Rch & RM=BECKYRN,Main            ,3624
     770     412     544     654    1070    1140
Boundary for River Rch & Prof#=BECKYRN,Main            , 1
Up Type= 0
Dn Type= 3
Dn Slope=0.04191
Boundary for River Rch & Prof#=BECKYRN,Main            , 2
Up Type= 0
Dn Type= 3
Dn Slope=0.04191
Boundary for River Rch & Prof#=BECKYRN,Main            , 3
Up Type= 0
Dn Type= 3
Dn Slope=0.04191
Boundary for River Rch & Prof#=BECKYRN,Main            , 4
Up Type= 0
Dn Type= 3
Dn Slope=0.04191
Boundary for River Rch & Prof#=BECKYRN,Main            , 5
Up Type= 0
Dn Type= 3
Dn Slope=0.04191
Boundary for River Rch & Prof#=BECKYRN,Main            , 6
Up Type= 0
Dn Type= 3
Dn Slope=0.04191
DSS Import GetInterval= 0
DSS Import GetPeak= 0
DSS Import FillOption= 0

--- BECKYRN.g01 (geometry) ---

Geom Title=USGS 10m DEM
Program Version=5.07

River Reach=BECKYRN         ,Main
Reach XY= 30
2120920.55300009414927.0390000052121136.28591994414947.768866207
2121712.96880416415283.6504743992121705.09600006415565.703000009
     2121914.258415706.6660000382122041.61603925 415671.20617616
2122243.99500008 416073.402000012122292.97500008416377.789000034
2122370.49100003 416407.206000032122556.94200002416368.147000015
2122690.30500007416422.0020000192122718.39000006416568.995000035
2122665.14800006416702.253000036      2122823.16 416924.52700001
2122853.10599999417305.9330000132122887.59100001417385.207000047
2123058.07840284417514.6525989922123029.39500004417652.689000025
2123169.11600006417851.5870000272123582.29100001418021.087000012
2123745.35000004418145.5360000282123957.84500003418179.359000027
2124024.03600009418292.8920000342123981.01200004418542.210000023
2124265.45100002418573.2850000112124460.97000004418739.474000037
     2124614.652418745.4960000072124837.34800005419073.697000012
2124873.28200004419269.1560000032125264.82449564419487.232268974

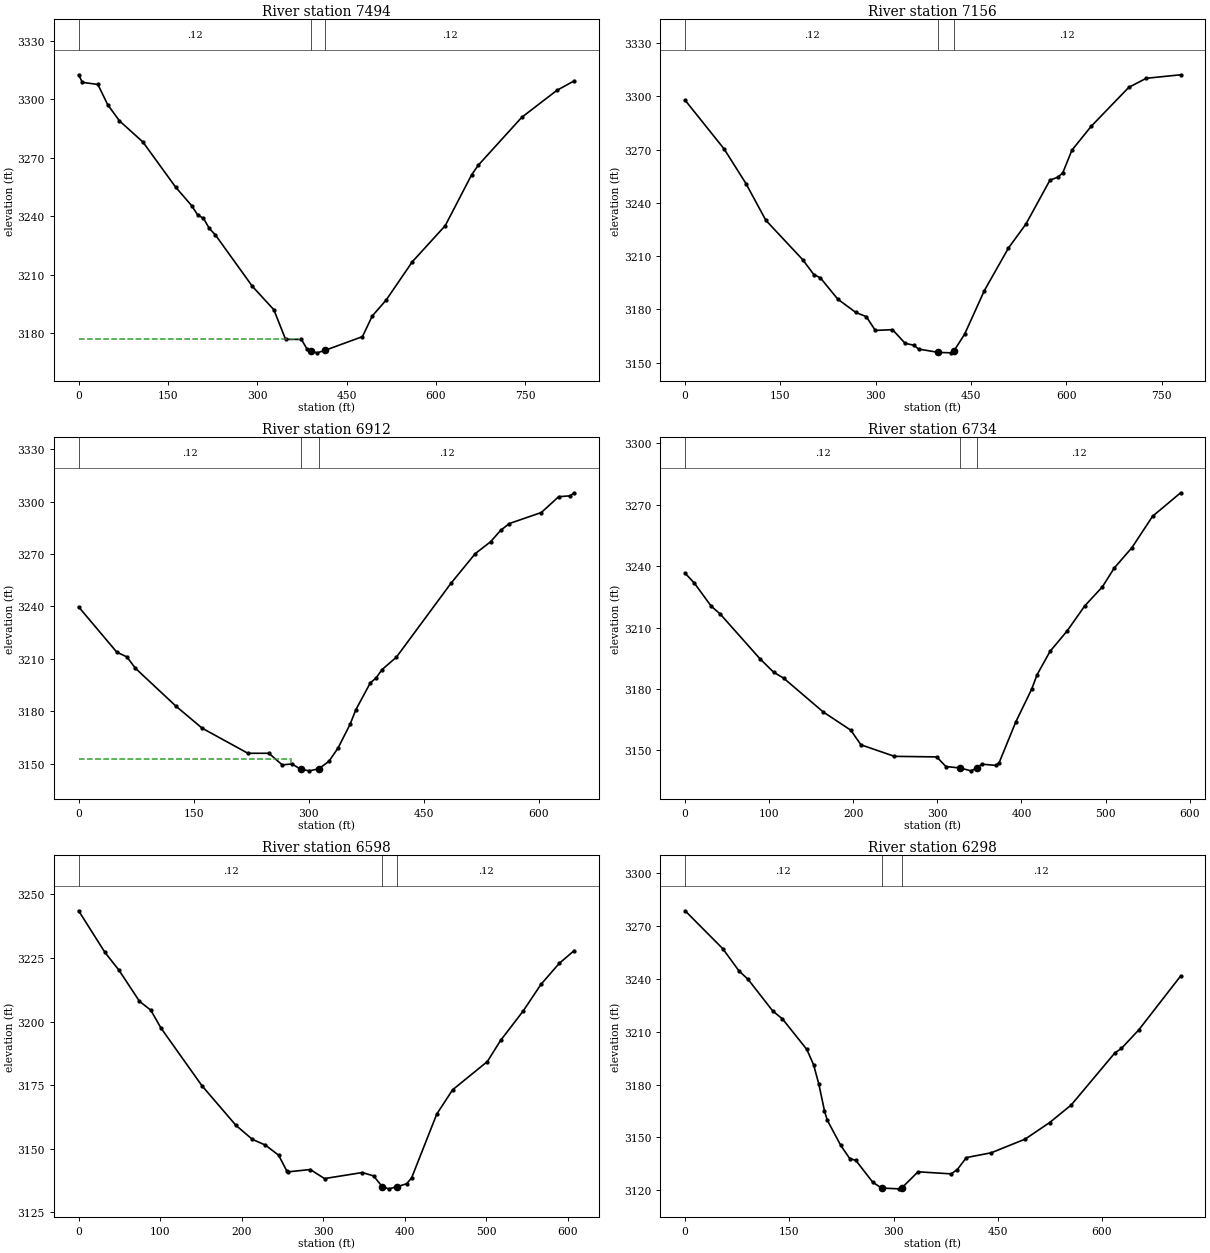
Type RM Length L Ch R = 1 ,7494    ,329.6,337.6,340.5
XS GIS Cut Line= 4
     2120939.855       415336.65      2120953.62       414981.51
     2120931.596      414819.081     2120788.438      414541.026
#Sta/Elev= 30
       0 3312.56     6.2 3308.69    32.3  3307.6    48.8 3297.24    68.5 3288.96
   107.9 3278.12     163 3254.93   189.9 3245.46   199.8 3240.78   209.6 3238.98
   219.5 3233.81   229.3 3230.64   291.7 3204.16   327.8 3192.15   347.5 3176.97
     374 3176.95   383.9 3171.85   389.5 3171.07   400.4 3170.06   413.7 3171.34
   476.6 3178.37   493.1 3188.97   516.3 3197.07   560.3 3216.73   615.6 3235.25
   659.9  3261.3     671 3266.19   744.1 3290.76     803 3304.56   832.1 3309.43
#Mann= 3 , 0 , 0
       0     .12       0   389.5     .04       0   413.7     .12       0
#XS Ineff= 2 , 0
          371.28    3177
Permanent Ineff=
       F       F
Bank Sta=389.5,413.7
XS Rating Curve= 0 ,0
Exp/Cntr=0.3,0.1

Type RM Length L Ch R = 1 ,7156    ,240.7,243.9,246
XS GIS Cut Line= 2
     2121140.826      415405.476     2121377.586      414662.159
#Sta/Elev= 30
       0 3297.82    61.4 3270.38    95.8 3250.89   127.1  3230.2   185.3 3207.96
   202.6 3199.67   212.9 3197.81   240.4 3185.79   268.7 3178.31   285.2 3175.96
   299.5 3168.18   326.5 3168.62   346.5 3160.88   359.6  3159.9   367.8 3157.67
   398.7 3155.81   419.2 3155.56   422.9 3156.44   440.1 3166.11   471.1  3190.6
     509 3214.56   536.6 3228.11   574.4 3252.82   586.8 3254.45   594.6 3256.96
   608.9 3269.65     639 3283.02   698.4 3305.04   725.9 3310.16   780.1 3312.14
#Mann= 3 , 0 , 0
       0     .12       0   398.7     .04       0   422.9     .12       0
Bank Sta=398.7,422.9
XS Rating Curve= 0 ,0
Exp/Cntr=0.3,0.1

Type RM Length L Ch R = 1 ,6912    ,179.7,178,176.8
XS GIS Cut Line= 2
 2121304.1209311415424.4948065752121624.16562999414863.624393672
#Sta/Elev= 30
       0 3239.75    49.8 3213.81    62.8 3211.16    74.1 3204.58     127 3182.87
     161 3170.33   220.6 3155.98   247.9 3155.98   265.4 3149.33   278.1 3149.89
   289.4  3146.8   300.8 3145.93   313.3 3147.15   326.4 3151.48   338.2 3159.09
   353.7 3172.51   361.2 3180.81   380.1 3196.25   387.7 3199.11   395.2 3203.78
   414.1 3210.96   485.1 3253.17   516.9 3270.23   536.8 3276.98     550 3283.54
   561.4 3287.45     603 3293.75   625.6 3302.79   640.7  3303.3   645.8 3305.04
#Mann= 3 , 0 , 0
       0     .12       0   289.4     .04       0   313.3     .12       0
#XS Ineff= 2 , 0
          276.96 3152.95
Permanent Ineff=
       F       F
Bank Sta=289.4,313.3
XS Rating Curve= 0 ,0
Exp/Cntr(USF)=0,0
Exp/Cntr=0.3,0.1

Type RM Length L Ch R = 1 ,6734    ,129.4,136.6,137.3
XS GIS Cut Line= 3
     2121424.387      415534.868     2121589.569      415298.108
     2121696.937      415017.299
#Sta/Elev= 30
       0 3236.54    11.1 3231.67    31.1  3220.4    41.7 3216.62    88.8 3194.83
   105.3 3188.16   117.1  3185.3   164.2 3168.77   197.1 3159.82   209.1  3152.7
     249 3147.06   299.3 3146.79   310.1 3142.08   327.3 3141.36     340 3139.98
   346.9 3141.34   352.7 3143.26   369.8 3142.62   373.3 3143.79   393.3 3163.91
     412 3179.76   418.7 3187.04     434 3198.36   454.3 3208.32   475.2 3220.53
   496.3 3229.92   510.3 3239.05   531.4 3249.04     556  3264.4   589.3 3275.84
#Mann= 3 , 0 , 0
       0     .12       0   327.3     .04       0   346.9     .12       0
Bank Sta=327.3,346.9
XS Rating Curve= 0 ,0
Exp/Cntr=0.3,0.1

Type RM Length L Ch R = 1 ,6598    ,293.8,299.5,281
XS GIS Cut Line= 3
2121464.93315503415593.6950358082121606.52017141415413.869190191
2121885.56027667415157.565686093
#Sta/Elev= 30
       0 3243.57    32.2 3227.23    49.7  3220.1    74.6 3207.97    88.5 3204.47
     101 3197.43   151.1  3174.8   192.9 3159.16   213.2 3153.61   228.9 3151.42
   245.3 3147.41   255.1 3141.33   257.4 3140.87   284.1 3141.77   301.6 3138.21
     348 3140.59   361.7 3139.26   372.73134.941   380.5 3134.17   390.8 3135.03
   402.2 3136.15   408.4 3138.46   439.3 3163.61   458.7 3173.14   501.3 3184.24
   517.5 3192.54   545.4  3204.2   567.1 3214.62   589.5 3222.89   607.8  3227.9
#Mann= 3 , 0 , 0
       0     .12       0   372.7     .04       0   390.8     .12       0
#XS Ineff= 2 , 0
          347.74 3140.44
Permanent Ineff=
       F       F
Bank Sta=372.7,390.8
XS Rating Curve= 0 ,0
Exp/Cntr(USF)=0,0
Exp/Cntr=0.3,0.1

Type RM Length L Ch R = 1 ,6298    ,140.8,140.8,137.4
XS GIS Cut Line= 2
     2121534.508      415804.664     2122013.534      415276.084
#Sta/Elev= 30
       0 3278.67    54.3 3257.13    77.5 3244.56    90.8 3239.68   126.2 3221.77
   140.2 3217.27   175.2 3199.96     185 3191.24   192.6 3180.11   200.6 3165.21
   204.5 3159.91   223.8 3145.67   236.9 3138.04   245.7    3137   270.3  3124.5
   282.9 3121.28   307.4 3120.83     312 3121.39   335.3  3130.5     383 3129.33
   391.9  3131.8   404.9 3138.58   440.6 3141.29   489.3 3149.02   524.7 3158.44
   555.7 3168.39   618.7 3198.02     628  3200.5   653.1 3211.09   713.3 3241.64
#Mann= 3 , 0 , 0
       0     .12       0   282.9     .04       0     312     .12       0
Bank Sta=282.9,312
XS Rating Curve= 0 ,0
Exp/Cntr=0.3,0.1

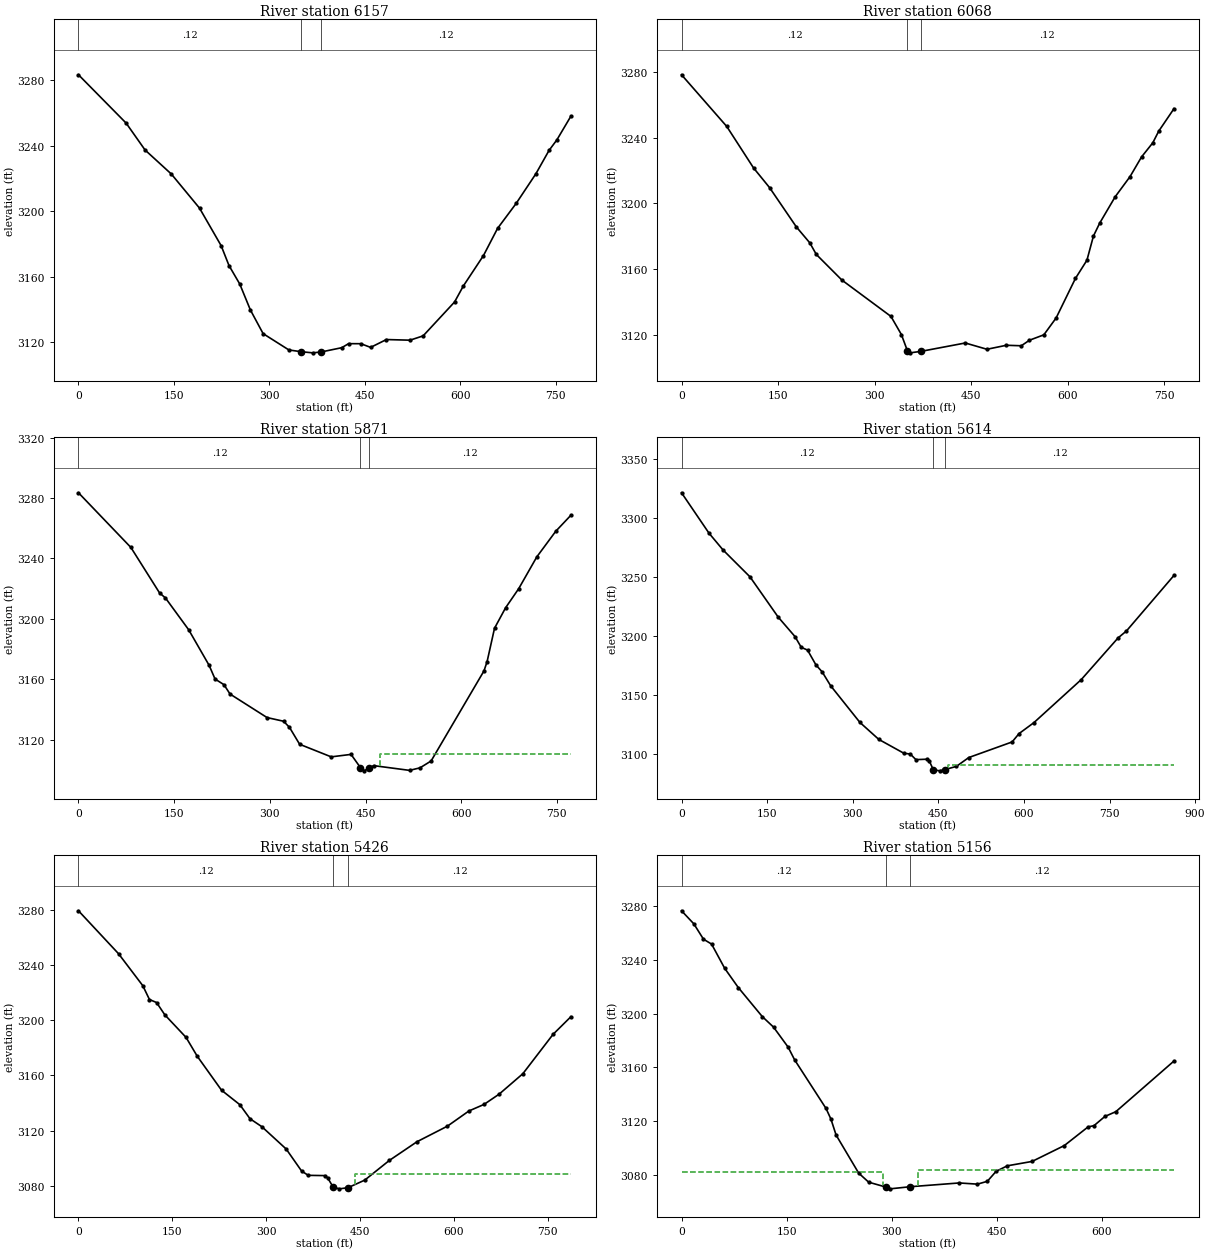
Type RM Length L Ch R = 1 ,6157    ,97.4,89.5,78.5
XS GIS Cut Line= 2
2121619.95543573415958.5141363982122088.12272346415342.558941067
#Sta/Elev= 30
       0 3283.41    74.9 3253.84   104.6 3237.41   145.9  3222.7   190.2 3201.83
   224.2 3178.85   236.5 3166.71   253.4 3155.43   270.1 3139.56   290.1 3125.08
   330.6  3115.1   349.4 3114.06   367.7 3113.34   380.8 3113.83   413.7 3116.49
   424.3 3118.95   443.6 3118.93     459 3116.68   483.8 3121.47   520.9 3121.08
   541.5 3123.72   590.9 3144.45   604.6 3154.18   636.3 3172.85   658.4 3189.43
   687.6 3204.69   718.7 3222.89   739.3 3237.14   751.6 3243.57   773.7 3258.11
#Mann= 3 ,-1 , 0
       0     .12       0   349.4     .04       0   380.8     .12       0
Bank Sta=349.4,380.8
XS Rating Curve= 0 ,0
Exp/Cntr(USF)=0,0
Exp/Cntr=0.3,0.1

Type RM Length L Ch R = 1 ,6068    ,178.4,197.2,202.1
XS GIS Cut Line= 4
2121721.89283807416006.0894464272121915.48807878415758.103161903
2121929.31631026415624.430257605 2122161.6305991 415409.63172863
#Sta/Elev= 30
       0 3278.19    70.3 3246.76   111.9 3221.56   136.9 3209.54   178.5 3185.66
   199.3 3176.02   209.5 3168.94   249.3 3153.34   325.5 3131.26   341.7 3120.25
   351.13110.329   355.2 3109.12   371.9    3110     441 3115.11   474.7 3111.29
   504.9 3113.72   528.1 3113.42   540.7 3116.78   563.1 3120.07   582.2 3130.32
   612.2 3154.35   630.1 3165.44   640.2 3180.13   649.9 3187.96     674 3204.02
   697.1 3216.28     715 3228.25   732.5 3236.85   741.7 3243.93   765.4 3257.59
#Mann= 3 , 0 , 0
       0     .12       0   351.1     .04       0   371.9     .12       0
#XS Ineff= 2 , 0
                          442.76         3114.82
Permanent Ineff=
       F       F
Bank Sta=351.1,371.9
XS Rating Curve= 0 ,0
Exp/Cntr(USF)=0,0
Exp/Cntr=0.3,0.1

Type RM Length L Ch R = 1 ,5871    ,252.7,256.4,258
XS GIS Cut Line= 4
2121741.25236214416041.120966174 2122031.6452232415747.040576719
2122146.88048553415655.7742489582122314.66302747415526.710755153
#Sta/Elev= 30
       0 3283.54    82.2  3247.3   127.1 3217.19   136.4 3213.82   172.7 3192.82
   204.8 3169.22   214.1 3160.14   228.1 3156.39   237.6 3150.19   295.6 3134.61
   321.5 3132.17   330.8 3128.11   346.7 3116.91   396.2 3108.57   427.3 3110.21
     442 3101.46   448.2 3099.31     456 3101.51     463 3102.75     519 3099.62
   535.4  3101.3   552.8 3105.84   635.7 3165.52   640.6  3171.7   652.2 3193.76
   669.6 3207.37   690.1 3219.99   718.5 3241.05   748.2 3258.03     772 3268.67
#Mann= 3 , 0 , 0
       0     .12       0     442     .04       0     456     .12       0
#XS Ineff= 2 , 0
                          472.13         3110.48
Permanent Ineff=
       F       F
Bank Sta=442,456
XS Rating Curve= 0 ,0
Exp/Cntr(USF)=0,0
Exp/Cntr=0.3,0.1

Type RM Length L Ch R = 1 ,5614    ,186.7,188.2,194
XS GIS Cut Line= 2
 2121763.3413966416154.0546968432122534.17472994415766.033863485
#Sta/Elev= 30
       0  3321.3    48.2    3287    72.9 3272.74     120 3250.01   169.4  3215.9
   198.8 3199.42   209.8 3190.27   220.8 3187.96   235.5 3175.41   246.5 3169.43
   261.2 3157.79   312.6 3126.63   345.7 3112.24   389.8 3100.45   400.8 3099.87
   410.7  3095.1   430.5 3095.45   433.9 3094.21   441.2 3086.59   452.2 3085.59
   461.63086.677   481.6 3089.34   503.4 3096.87   579.3 3110.07   591.5 3117.17
   617.5 3126.45   700.5 3162.94     765 3198.26   779.7 3204.16     863 3251.25
#Mann= 3 , 0 , 0
       0     .12       0   441.2     .04       0   461.6     .12       0
#XS Ineff= 2 , 0
                          467.17          3090.7
Permanent Ineff=
       F       F
Bank Sta=441.2,461.6
XS Rating Curve= 0 ,0
Exp/Cntr(USF)=0,0
Exp/Cntr=0.3,0.1

Type RM Length L Ch R = 1 ,5426    ,279.3,269.8,260.6
XS GIS Cut Line= 4
     2121864.871       416256.16     2122208.999      416121.262
     2122349.404      416099.238     2122610.941      416013.894
#Sta/Elev= 30
       0 3279.13      64 3248.08   102.8 3224.94   113.4 3214.96   124.8 3212.76
     138 3203.86   171.9 3187.55   189.8 3173.92   228.6 3149.35   257.8  3138.9
   274.1 3128.72   293.1 3122.94   331.9 3106.82   356.5 3090.92   367.1 3087.78
   393.8 3087.59   398.3 3085.85   407.1 3079.19     417 3078.02   430.7 3078.86
   457.4 3084.31   496.7 3098.55     541 3112.11   589.6 3123.37   623.9 3134.34
     648 3139.07   672.2 3146.51   710.1 3161.29   758.4 3189.78   786.9 3202.53
#Mann= 3 , 0 , 0
       0     .12       0   407.1     .04       0   430.7     .12       0
#XS Ineff= 2 , 0
                          441.55         3088.51
Permanent Ineff=
       F       F
Bank Sta=407.1,430.7
XS Rating Curve= 0 ,0
Exp/Cntr=0.3,0.1

Type RM Length L Ch R = 1 ,5156    ,330,318.6,318
XS GIS Cut Line= 2
2122051.94814831416571.5857075392122596.97476423416127.959392249
#Sta/Elev= 30
       0 3276.78    17.6 3267.01    31.3  3255.6    42.9 3251.94    61.6 3233.87
      81 3219.55   115.2 3197.93   131.3 3190.05   152.1 3175.15   161.4 3165.65
   206.2 3129.43   213.2 3121.52   220.6 3109.58   252.8 3081.24   267.1 3074.46
   292.4 3070.73   297.6 3069.51   326.4 3071.09   396.3  3073.9   422.3 3073.01
   436.4 3075.12     449 3082.58     465 3086.68   500.3 3089.94   546.3 3101.77
   580.2 3115.68   588.6 3116.59   604.2 3123.47   619.8 3127.02   702.8  3164.8
#Mann= 3 , 0 , 0
       0     .12       0   292.4     .04       0   326.4     .12       0
#XS Ineff= 2 , 0
          287.81 3081.86  337.49         3083.44
Permanent Ineff=
       F       F
Bank Sta=292.4,326.4
XS Rating Curve= 0 ,0
Exp/Cntr(USF)=0,0
Exp/Cntr=0.3,0.1

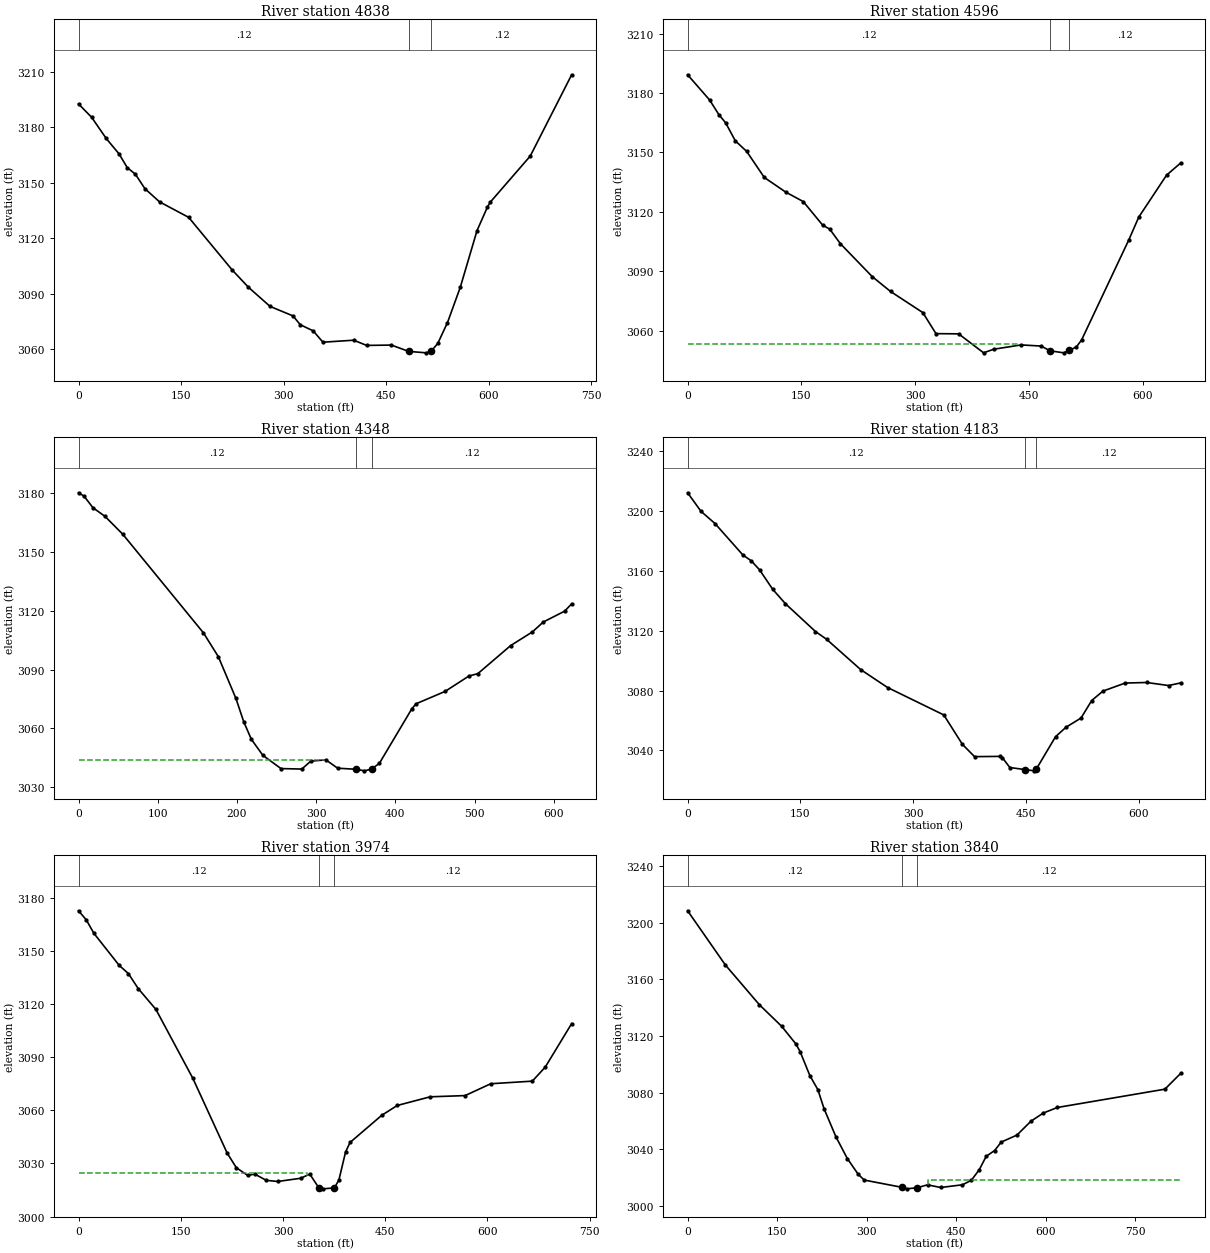
Type RM Length L Ch R = 1 ,4838    ,235.4,241.7,258.5
XS GIS Cut Line= 3
     2122324.626      416787.494     2122627.459      416333.245
     2122756.851      416214.865
#Sta/Elev= 30
       0 3192.69    19.2 3185.47    40.5 3174.01    59.4 3165.61    71.2 3158.27
    83.1  3154.7    97.2 3146.82   118.5 3139.71   161.1 3131.32     225 3102.74
   248.6 3093.47   280.2 3083.12   313.7 3077.99   324.4 3073.21   343.3 3069.88
   357.5 3063.76   402.5 3064.84   421.4 3062.02   457.7  3062.2   482.9 3058.78
   508.9    3058     516 3058.99   525.5  3063.1   539.7 3074.38   558.4 3093.47
   582.9 3124.15   598.1 3136.88   602.4  3139.6   660.7 3164.46   721.3 3208.47
#Mann= 3 , 0 , 0
       0     .12       0   482.9     .04       0     516     .12       0
Bank Sta=482.9,516
XS Rating Curve= 0 ,0
Exp/Cntr=0.3,0.1

Type RM Length L Ch R = 1 ,4596    ,248.7,247.9,241.2
XS GIS Cut Line= 3
2122338.84640471416802.8178233112122524.93704875416578.878234715
2122881.34794328416534.721132738
#Sta/Elev= 30
       0 3189.22      29  3176.5    41.5 3168.95    50.1 3164.99    62.9 3155.89
    77.9 3150.54   101.1  3137.4   129.2 3130.05   152.5 3125.23     178 3113.37
   187.4 3111.33   201.4    3104   243.3 3087.41   267.6 3079.86   310.2 3069.19
   327.5 3058.58   357.4 3058.47   390.3  3048.9   403.5  3050.7   439.9 3052.89
   466.1 3052.31     478 3049.91   496.1 3048.89   503.33050.077   512.6 3051.86
   519.5 3055.36     582 3106.06   594.9 3117.37   631.6 3138.58   650.3 3144.73
#Mann= 3 , 0 , 0
       0     .12       0     478     .04       0   503.3     .12       0
#XS Ineff= 2 , 0
          437.39 3053.52
Permanent Ineff=
       F       F
Bank Sta=478,503.3
XS Rating Curve= 0 ,0
Exp/Cntr(USF)=0,0
Exp/Cntr=0.3,0.1

Type RM Length L Ch R = 1 ,4348    ,164.1,164.5,164.5
XS GIS Cut Line= 2
     2122407.217       416947.17     2122949.563      416641.584
#Sta/Elev= 30
       0 3180.02       7  3178.3    18.3 3172.38    33.4 3168.03      56 3158.85
   157.7  3108.7   176.5 3096.57   198.7 3075.32   208.6 3063.38   218.2 3054.49
   232.7 3046.34   255.6 3039.59   281.9 3039.35   293.2 3043.37   312.2 3044.05
   327.1 3039.78   350.2 3039.24     361 3038.44     370 3039.34   379.8 3042.27
   420.6 3069.92     426 3072.57   462.7 3078.87   492.8 3086.72   504.1 3087.93
   545.5 3102.22     573 3109.19   586.7 3114.22   613.6 3119.73   622.5 3123.47
#Mann= 3 , 0 , 0
       0     .12       0   350.2     .04       0     370     .12       0
#XS Ineff= 2 , 0
          311.02  3044.2
Permanent Ineff=
       F       F
Bank Sta=350.2,370
XS Rating Curve= 0 ,0
Exp/Cntr=0.3,0.1

Type RM Length L Ch R = 1 ,4183    ,206.4,209.9,213.4
XS GIS Cut Line= 2
2122404.14559291417121.435644957 2122983.9076608416814.248280628
#Sta/Elev= 30
       0 3212.31    17.8 3199.91    36.4 3191.76    73.5 3170.73    84.7  3166.8
    95.8 3160.73   113.2 3147.75   130.2 3138.09   170.1 3119.52   184.9 3114.33
   230.2 3094.08   266.1 3082.06   340.8 3063.74   365.6 3044.08   381.7 3035.85
   415.1 3036.01   418.8 3035.13   428.7 3028.57   448.5 3027.21   461.5 3026.35
   463.93027.496   489.5 3049.18   503.5 3055.54   523.4 3061.65   537.6 3073.36
   552.5 3079.66   582.2 3085.07   610.8 3085.43   639.9  3083.4   656.1 3085.17
#Mann= 3 , 0 , 0
       0     .12       0   448.5     .04       0   463.9     .12       0
Bank Sta=448.5,463.9
XS Rating Curve= 0 ,0
Exp/Cntr(USF)=0,0
Exp/Cntr=0.3,0.1

Type RM Length L Ch R = 1 ,3974    ,128.5,133.8,139.8
XS GIS Cut Line= 4
2122493.02235571417185.5107076682122818.29960607417108.919262088
2122906.23793248417107.0281152842123156.81488406 416939.66162309
#Sta/Elev= 30
       0 3172.82    11.2 3167.79    22.6 3160.07    59.7 3141.96    73.2 3137.31
    87.6 3128.86   113.6 3117.04   167.6 3078.24   218.1 3035.87   231.6 3027.59
   248.4 3023.22   258.6 3024.02   275.4 3020.48   292.2 3019.82     326 3021.65
   339.3    3024   352.7 3016.17     359 3015.67   375.4 3016.22     382 3020.63
   391.8 3036.48   398.4 3041.89   444.9 3057.24   467.6 3062.78   515.9 3067.68
   567.2 3068.37   604.8 3075.07   665.8 3076.53   684.8  3084.5   723.5 3109.05
#Mann= 3 , 0 , 0
       0     .12       0   352.7     .04       0   375.4     .12       0
#XS Ineff= 2 , 0
          334.78 3024.66
Permanent Ineff=
       F       F
Bank Sta=352.7,375.4
XS Rating Curve= 0 ,0
Exp/Cntr=0.3,0.1

Type RM Length L Ch R = 1 ,3840    ,82.7,70.5,60.9
XS GIS Cut Line= 4
2122486.40334189417290.4693553152122793.71469761417217.660203343
2122891.10875804417263.9933000522123207.87584778 417016.25306867
#Sta/Elev= 30
       0 3208.48    63.1 3170.25   120.2 3142.09   157.6 3126.82   181.2 3114.45
   188.4 3108.96   204.7 3092.04   218.2 3082.01   228.4 3068.72   248.3 3048.84
   267.4 3033.45   285.7 3022.29   295.8 3018.23   359.1 3013.09   366.9 3012.03
   384.4 3012.82   401.7 3014.87   423.7 3012.98   460.3 3014.89   475.2  3018.1
   488.4 3025.58     500 3034.98   514.1 3039.11   525.2 3045.06   551.5 3050.01
   574.8 3059.78   595.7  3065.6   619.2 3069.51   799.2 3082.44   825.8 3093.64
#Mann= 3 , 0 , 0
       0     .12       0   359.1     .04       0   384.4     .12       0
#XS Ineff= 2 , 0
                          402.74         3017.93
Permanent Ineff=
       F       F
Bank Sta=359.1,384.4
XS Rating Curve= 0 ,0
Exp/Cntr=0.3,0.1

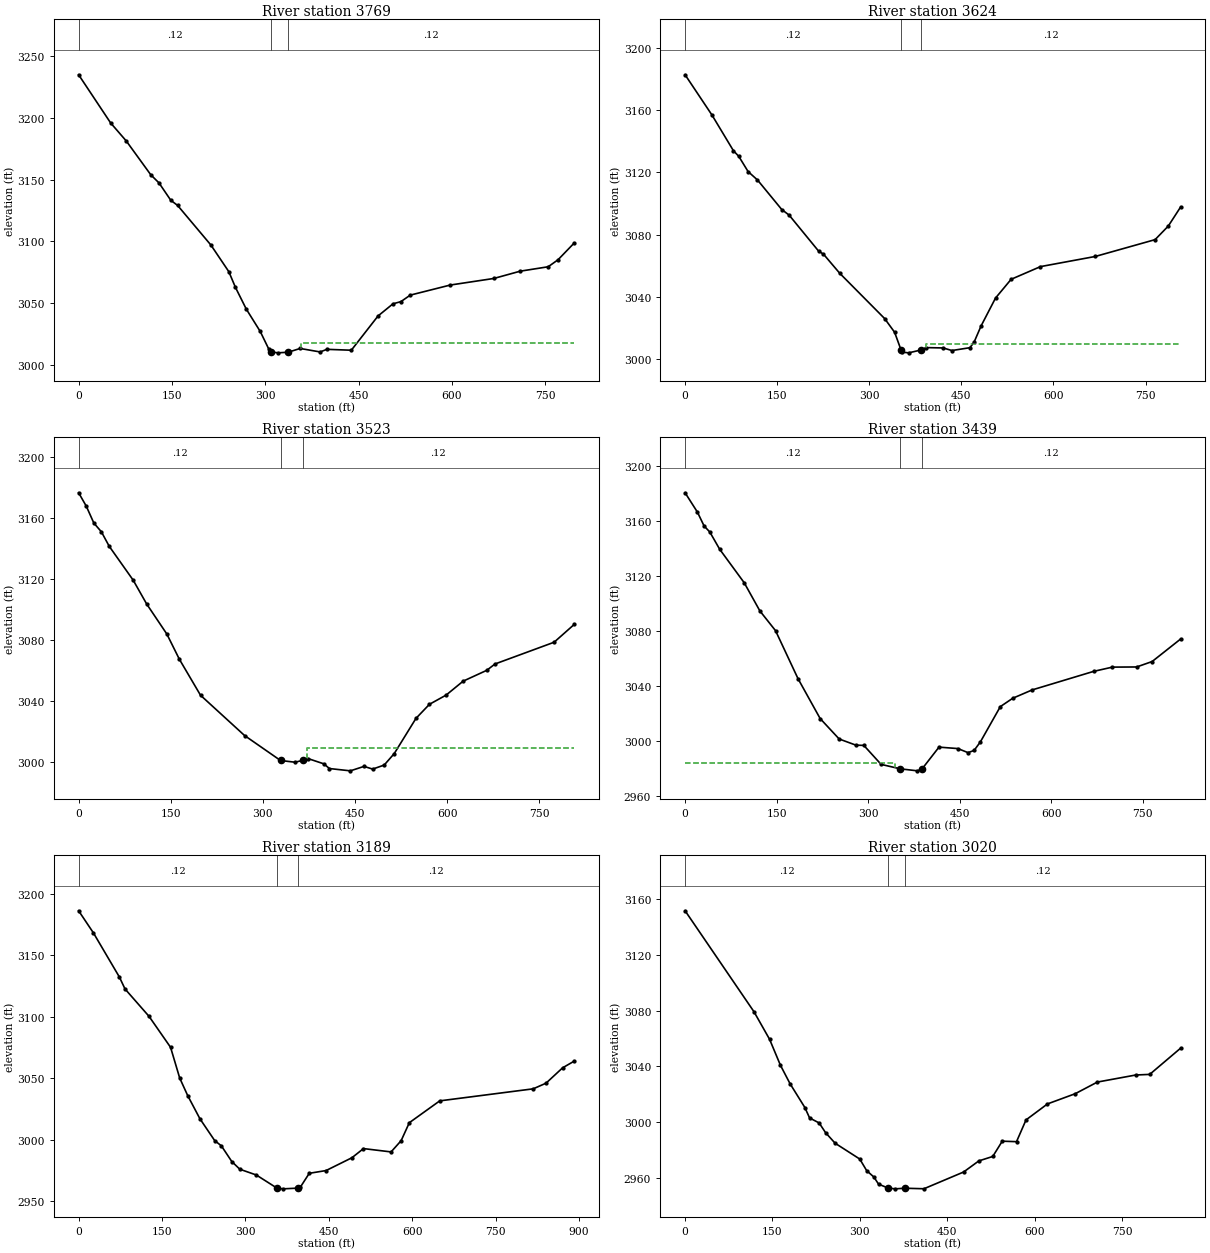
Type RM Length L Ch R = 1 ,3769    ,154.1,145.5,133.7
XS GIS Cut Line= 3
     2122553.127      417442.714     2123018.389       417238.99
      2123246.89      417062.797
#Sta/Elev= 30
       0  3234.5    51.5  3195.6    76.6 3181.07     116 3153.79   129.1 3147.29
   148.2 3133.19     159 3129.12   212.7 3097.06   241.4 3075.64   252.1 3062.91
   269.4  3045.5   291.9 3027.39   305.8    3013   309.3 3010.96   320.2 3010.14
   336.8 3010.64     356 3013.66   388.2 3010.86     399 3012.97   438.3 3012.25
   481.3 3039.92   505.3 3049.71   517.9 3051.44   533.1 3056.72   597.3 3064.84
   667.4 3070.16   709.7 3076.02   754.7 3079.59   770.5 3085.21   796.5 3098.73
#Mann= 3 , 0 , 0
       0     .12       0   309.3     .04       0   336.8     .12       0
#XS Ineff= 2 , 0
                          357.37         3018.38
Permanent Ineff=
       F       F
Bank Sta=309.3,336.8
XS Rating Curve= 0 ,0
Exp/Cntr=0.3,0.1

Type RM Length L Ch R = 1 ,3624    ,97.9,100.8,112.8
XS GIS Cut Line= 4
2122721.04102455417675.0929259232122941.48270771 417414.65549434
2123008.45233297417284.4367785492123252.14735824417077.947100651
#Sta/Elev= 30
       0 3182.56    43.8  3156.7    78.7 3133.83    87.4 3130.22   102.6 3120.44
   117.9 3115.04   157.4 3096.09   169.5 3092.46   217.5 3069.36   225.4 3067.43
   251.9 3055.14     325 3026.08   341.2 3017.32   351.6 3006.06     354 3004.52
   364.2 3004.09   384.4 3005.94     393 3007.45   420.3 3007.23   434.6 3005.57
   463.8 3007.39   470.5 3010.79   482.2 3021.46   505.6 3039.25     531 3051.29
   578.8 3059.43     668 3065.94   765.5 3076.75     787 3085.47   807.1 3097.72
#Mann= 3 , 0 , 0
       0     .12       0   351.6     .04       0   384.4     .12       0
#XS Ineff= 2 , 0
                          393.13         3009.75
Permanent Ineff=
       F       F
Bank Sta=351.6,384.4
XS Rating Curve= 0 ,0
Exp/Cntr(USF)=0,0
Exp/Cntr=0.3,0.1

Type RM Length L Ch R = 1 ,3523    ,76.8,84.1,93.1
XS GIS Cut Line= 2
2122734.70273794417683.616644268 2123381.1270458417200.681934081
#Sta/Elev= 30
       03176.601  12.4743167.815   24.763156.784  37.0463151.043  49.8183141.551
   88.843119.362 110.764 3103.78 143.6573084.077 164.0013067.602 198.4743044.005
 270.1623017.642 328.7643001.271 352.3853000.147 364.671 3001.33 373.8893002.484
 399.086 2999.11 408.462    2996 442.4822994.499  464.722997.412 478.7852995.646
 497.5382998.281 513.9463005.817 549.3043028.853 571.2313038.075 598.3333044.089
 626.0483053.213  664.423060.303 678.0323064.485 774.2033078.719 806.9023090.355
#Mann= 3 , 0 , 0
       0     .12       0 328.764     .04       0 364.671     .12       0
#XS Ineff= 2 , 0
                          372.26         3009.56
Permanent Ineff=
       F       F
Bank Sta=328.764,364.671
XS Rating Curve= 0 ,0
Exp/Cntr(USF)=0,0
Exp/Cntr=0.3,0.1

Type RM Length L Ch R = 1 ,3439    ,255,249.6,232.7
XS GIS Cut Line= 4
2122767.69167414417706.6256763392122992.64006034417548.594744869
 2123225.1734814417516.0400659212123435.38369403417330.013329076
#Sta/Elev= 30
       0 3180.53    20.2 3166.48    31.1 3156.44    40.5 3152.04    56.7  3139.5
    96.9 3115.17   122.6 3094.69   148.2  3080.4   185.1 3045.48   221.3 3016.57
   252.5 3001.71   279.9 2997.24   292.9 2997.06   321.2 2983.27   352.72980.035
   380.8 2978.58   388.1 2979.85   416.1  2995.8   447.1 2994.75   463.6 2991.81
   473.6 2993.38     484 2999.66   516.6 3025.22     537 3031.31   568.9 3037.37
   669.6 3050.83   700.3 3053.91     740 3054.02   765.4 3057.97   812.1 3074.33
#Mann= 3 , 0 , 0
       0     .12       0   352.7     .04       0   388.1     .12       0
#XS Ineff= 2 , 0
          344.33 2984.47
Permanent Ineff=
       F       F
Bank Sta=352.7,388.1
XS Rating Curve= 0 ,0
Exp/Cntr(USF)=0,0
Exp/Cntr=0.3,0.1

Type RM Length L Ch R = 1 ,3189    ,169.5,168.7,163.8
XS GIS Cut Line= 2
     2122811.912      418004.331     2123475.391      417409.678
#Sta/Elev= 30
       0 3186.08    26.7 3168.03    73.1 3132.42    83.4 3122.59   126.6 3100.34
   165.3 3075.21   181.7 3050.29   196.1    3036   218.1 3017.17   244.6 2999.49
   256.7 2995.16   275.4 2982.45   289.8 2976.21   319.5 2971.52   356.6 2960.87
   367.9 2960.28   394.4 2960.86   398.8 2961.75   414.7  2972.9   444.9 2975.13
   491.4 2985.54   512.2 2992.97   561.8 2990.26   579.9 2999.41   594.6 3013.99
   649.3 3031.72   817.3 3041.49   840.4 3046.08   870.2 3058.55     891 3063.97
#Mann= 3 , 0 , 0
       0     .12       0   356.6     .04       0   394.4     .12       0
Bank Sta=356.6,394.4
XS Rating Curve= 0 ,0
Exp/Cntr=0.3,0.1

Type RM Length L Ch R = 1 ,3020    ,196.1,198.4,194.3
XS GIS Cut Line= 2
2122992.56082599418159.8154680432123498.77098974417476.215417845
#Sta/Elev= 30
       0 3151.87   118.3 3079.22     145 3059.46   163.7 3040.74   180.1 3027.55
   205.6 3010.37   213.7 3002.89   230.1 2999.29   241.1 2992.33   257.5 2984.72
   299.8 2973.34   311.7    2965     324 2960.41   332.1 2955.29   348.4 2952.48
   360.7 2951.91     377 2952.35     410 2951.97     478    2964   504.2    2972
   528.1 2975.19   544.4 2986.18   568.9 2985.83   585.2 3001.48     622 3012.97
   669.6 3020.31   707.7  3028.7   773.6 3033.77   797.5 3034.21   850.6 3053.08
#Mann= 3 , 0 , 0
       0     .12       0   348.4     .04       0     377     .12       0
Bank Sta=348.4,377
XS Rating Curve= 0 ,0
Exp/Cntr(USF)=0,0
Exp/Cntr=0.3,0.1

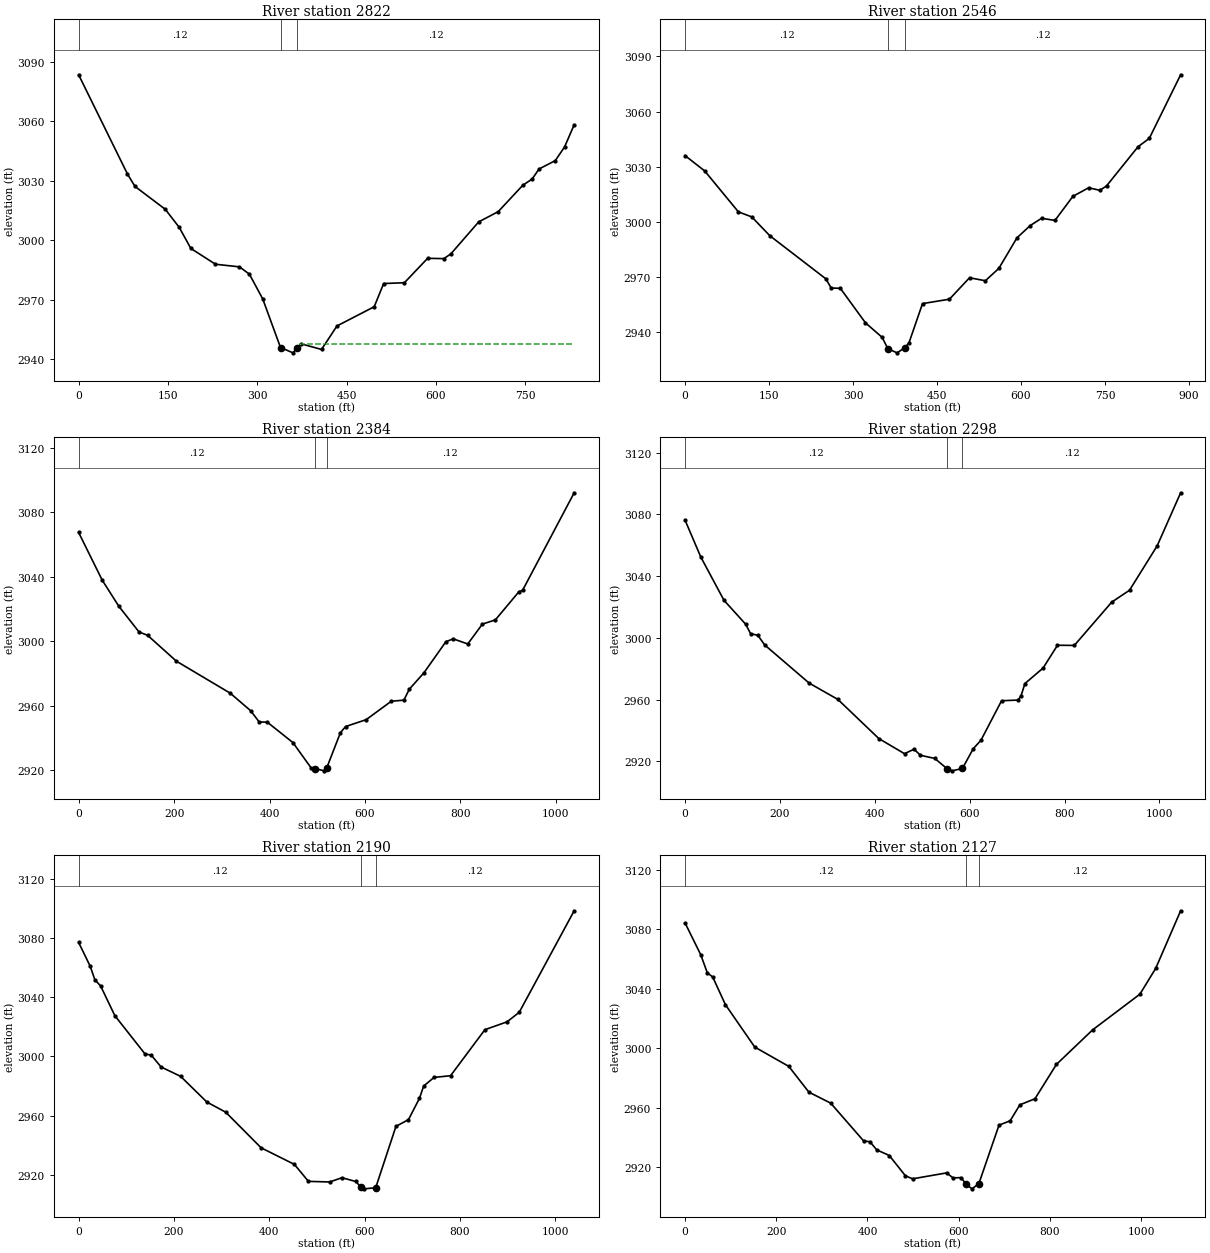
Type RM Length L Ch R = 1 ,2822    ,275.1,275.9,276.6
XS GIS Cut Line= 2
2123199.03904927418235.1843898762123649.00288335417534.888563597
#Sta/Elev= 30
       0 3083.56      82 3033.51    94.6 3027.26   145.6 3015.69     169 3006.58
   188.5 2995.96   229.9 2987.99   270.2 2986.67   286.9 2982.97   309.3 2970.46
   339.1 2945.99     360  2943.3   367.6 2945.94   373.4 2947.87     408 2945.01
     434 2956.87   496.5 2966.56   512.4 2978.26   547.2 2978.66   586.2 2990.97
   613.5 2990.83   625.2 2993.19     672 3009.35   704.8 3014.52   746.1 3027.83
   761.8 3030.97   773.4 3036.04   800.7 3040.27   816.3 3047.18   832.4 3058.35
#Mann= 3 , 0 , 0
       0     .12       0   339.1     .04       0   367.6     .12       0
#XS Ineff= 2 , 0
                          371.71         2947.99
Permanent Ineff=
       F       F
Bank Sta=339.1,367.6
XS Rating Curve= 0 ,0
Exp/Cntr(USF)=0,0
Exp/Cntr=0.3,0.1

Type RM Length L Ch R = 1 ,2546    ,164.6,161.8,158.6
XS GIS Cut Line= 2
      2123420.33       418367.73      2123929.64      417643.685
#Sta/Elev= 30
       0 3036.06      35 3027.75    95.2 3005.49   119.2 3002.73   151.3 2992.52
   251.5 2969.06   260.9  2964.1   277.4 2963.89   322.1 2945.18   351.9 2937.28
   362.1 2931.14   378.6 2928.83     392 2931.49   399.8 2934.16   424.1  2955.6
   472.2    2958   508.1 2969.66   536.4 2968.03   560.5 2974.77   592.9  2991.4
   616.6 2998.06   636.7 3001.99   660.7 3000.84   692.8 3013.95   720.9 3018.58
     741 3017.21   752.8 3019.59   809.2 3040.93   829.2 3045.45   885.2 3080.03
#Mann= 3 , 0 , 0
       0     .12       0   362.1     .04       0     392     .12       0
Bank Sta=362.1,392
XS Rating Curve= 0 ,0
Exp/Cntr=0.3,0.1

Type RM Length L Ch R = 1 ,2384    ,85.9,85.9,85.7
XS GIS Cut Line= 4
2123482.95945218418560.3046968432123730.35528553418271.242196828
2123808.48028553418004.315113485 2124003.7927855417678.794280171
#Sta/Elev= 30
       0 3067.44    49.3 3037.92    83.9 3021.81   126.6 3005.69   144.3 3003.69
   204.8 2987.61   317.8 2967.72   360.2 2956.92   378.3 2949.92   395.2 2949.79
   448.9 2937.13   487.5 2921.23   495.2 2920.97   514.9 2919.59   519.4 2921.08
   548.4 2943.23   559.3 2947.07   602.3 2951.31     655 2962.75   681.4 2963.44
   692.9 2970.26   723.5 2980.42   769.4 2999.68   784.7 3001.46   815.3 2998.29
   845.9  3010.6   873.1 3013.22   922.4 3030.68   930.1 3031.55  1038.2 3092.06
#Mann= 3 , 0 , 0
       0     .12       0   495.2     .04       0   519.4     .12       0
Bank Sta=495.2,519.4
XS Rating Curve= 0 ,0
Exp/Cntr(USF)=0,0
Exp/Cntr=0.3,0.1

Type RM Length L Ch R = 1 ,2298    ,103.6,108.6,118.8
XS GIS Cut Line= 4
2123539.22889614418615.9479283942123826.30719374418268.902164184
2123869.68791427418069.8612111812124077.66019208417739.402193055
#Sta/Elev= 30
       0  3076.2    33.1 3052.38      82 3024.34   127.8 3008.84   137.9 3002.84
   153.5 3001.63   167.7 2995.47   261.6 2970.73   322.1 2960.17   408.3 2934.86
   462.5 2925.04   482.6 2927.95   496.1 2924.01   526.3 2921.98   552.2 2915.32
   563.2 2913.94   584.7 2915.52   607.3 2928.21   623.7 2933.76   667.1 2959.32
   701.8 2959.76   708.1 2962.42   716.3 2970.44   754.6 2980.47     785 2995.25
   820.5 2995.15   899.2 3023.14   936.8 3030.87     995 3059.55  1044.6 3093.98
#Mann= 3 , 0 , 0
       0     .12       0   552.2     .04       0   584.7     .12       0
Bank Sta=552.2,584.7
XS Rating Curve= 0 ,0
Exp/Cntr(USF)=0,0
Exp/Cntr=0.3,0.1

Type RM Length L Ch R = 1 ,2190    ,63.3,62.8,70.3
XS GIS Cut Line= 2
2123557.99695241418629.6683060172124245.03477881417849.507882673
#Sta/Elev= 30
       0 3076.96    24.3 3060.91    34.1 3051.76    46.2 3047.56    75.9  3027.6
   138.7 3001.93   152.7 3000.77     173 2992.91     214 2986.59   269.1 2969.23
   308.5 2962.42   382.8 2938.37   452.7 2927.16   482.1 2915.71   526.7 2915.31
   552.5 2918.18   581.3 2915.63     592 2911.99     599 2910.67   623.2 2911.42
   665.7 2952.83     692  2957.4     715 2971.73   723.8 2980.03   745.6 2985.87
   780.3 2987.03   852.3 3018.09   898.7 3023.38   924.4 3029.85  1039.6 3098.35
#Mann= 3 , 0 , 0
       0     .12       0     592     .04       0   623.2     .12       0
Bank Sta=592,623.2
XS Rating Curve= 0 ,0
Exp/Cntr(USF)=0,0
Exp/Cntr=0.3,0.1

Type RM Length L Ch R = 1 ,2127    ,97.5,96.3,107
XS GIS Cut Line= 3
2123568.57467767 418654.225034742123826.30719374418339.076859153
2124391.53246413417961.409409865
#Sta/Elev= 30
       0 3084.24    34.1 3063.05    48.8 3050.67    60.5 3047.99    88.4 3029.34
   152.8 3000.79   227.4 2987.81   271.5 2970.47   319.3 2963.07   391.5 2937.68
   405.5 2937.06   420.2 2931.66   447.9 2927.83   483.4 2914.11   499.2 2912.16
   573.4 2916.13   587.6 2912.78   605.7 2912.96     616 2908.45   629.4 2905.41
   644.4 2908.96   688.5 2948.24     713  2951.2   734.3 2961.95   767.3 2965.98
   814.5 2989.14   893.7 3012.33   997.6 3036.38  1032.3  3053.8  1086.9 3092.49
#Mann= 3 , 0 , 0
       0     .12       0     616     .04       0   644.4     .12       0
Bank Sta=616,644.4
XS Rating Curve= 0 ,0
Exp/Cntr(USF)=0,0
Exp/Cntr=0.3,0.1