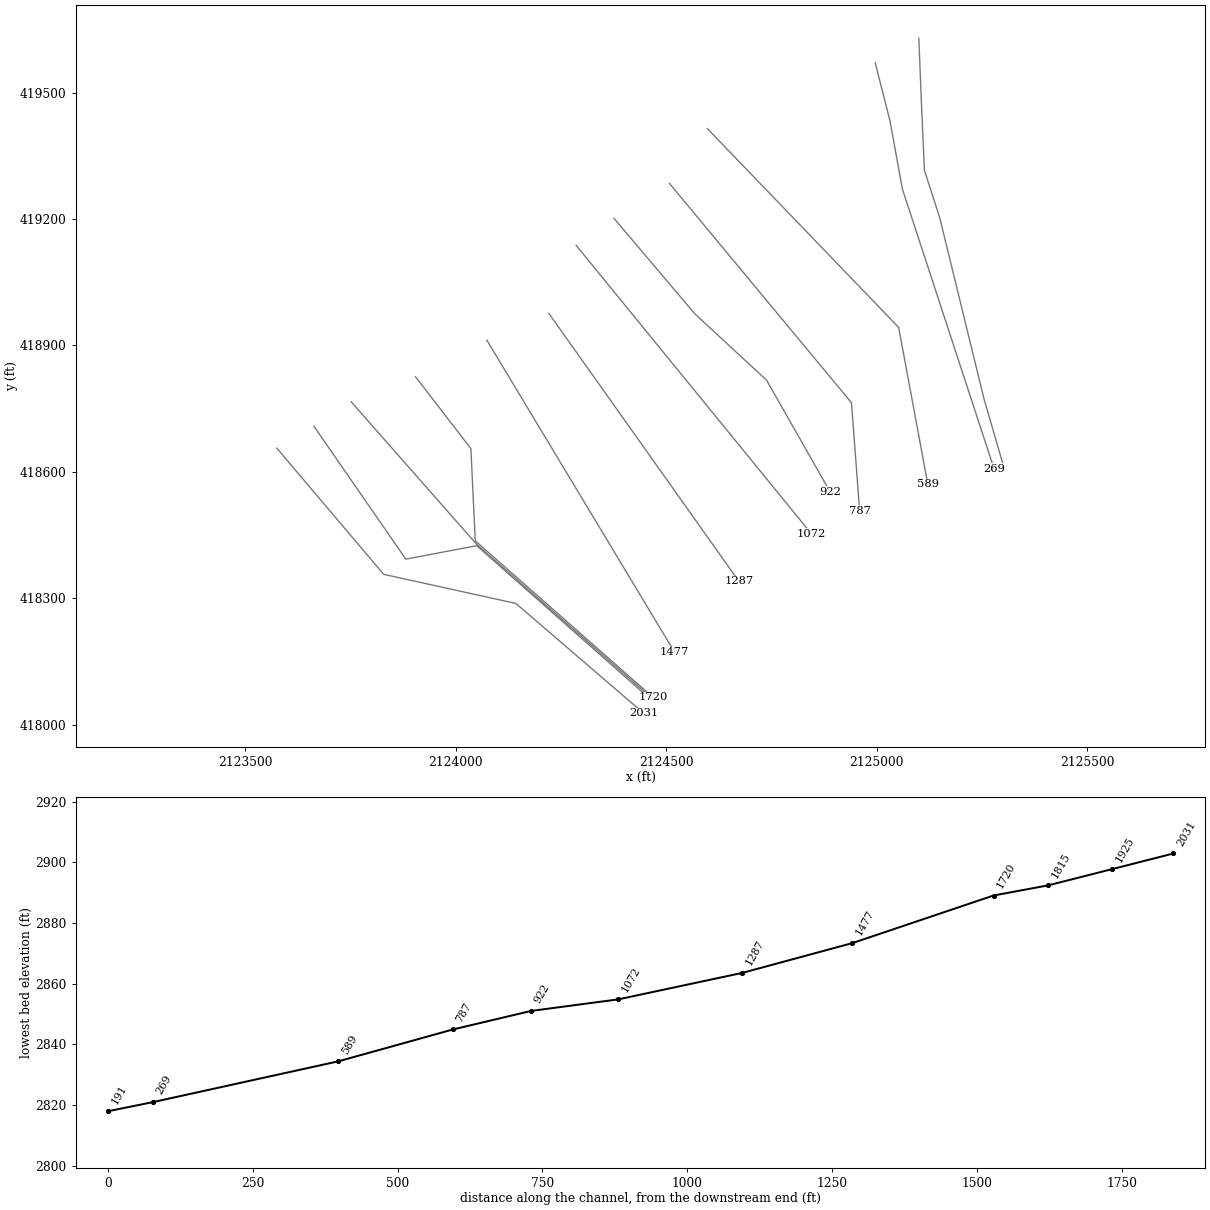
HEC-RAS study BECKYRN.prj: BECKYRN

--- BECKYRN.g01 (geometry) --- (continued)

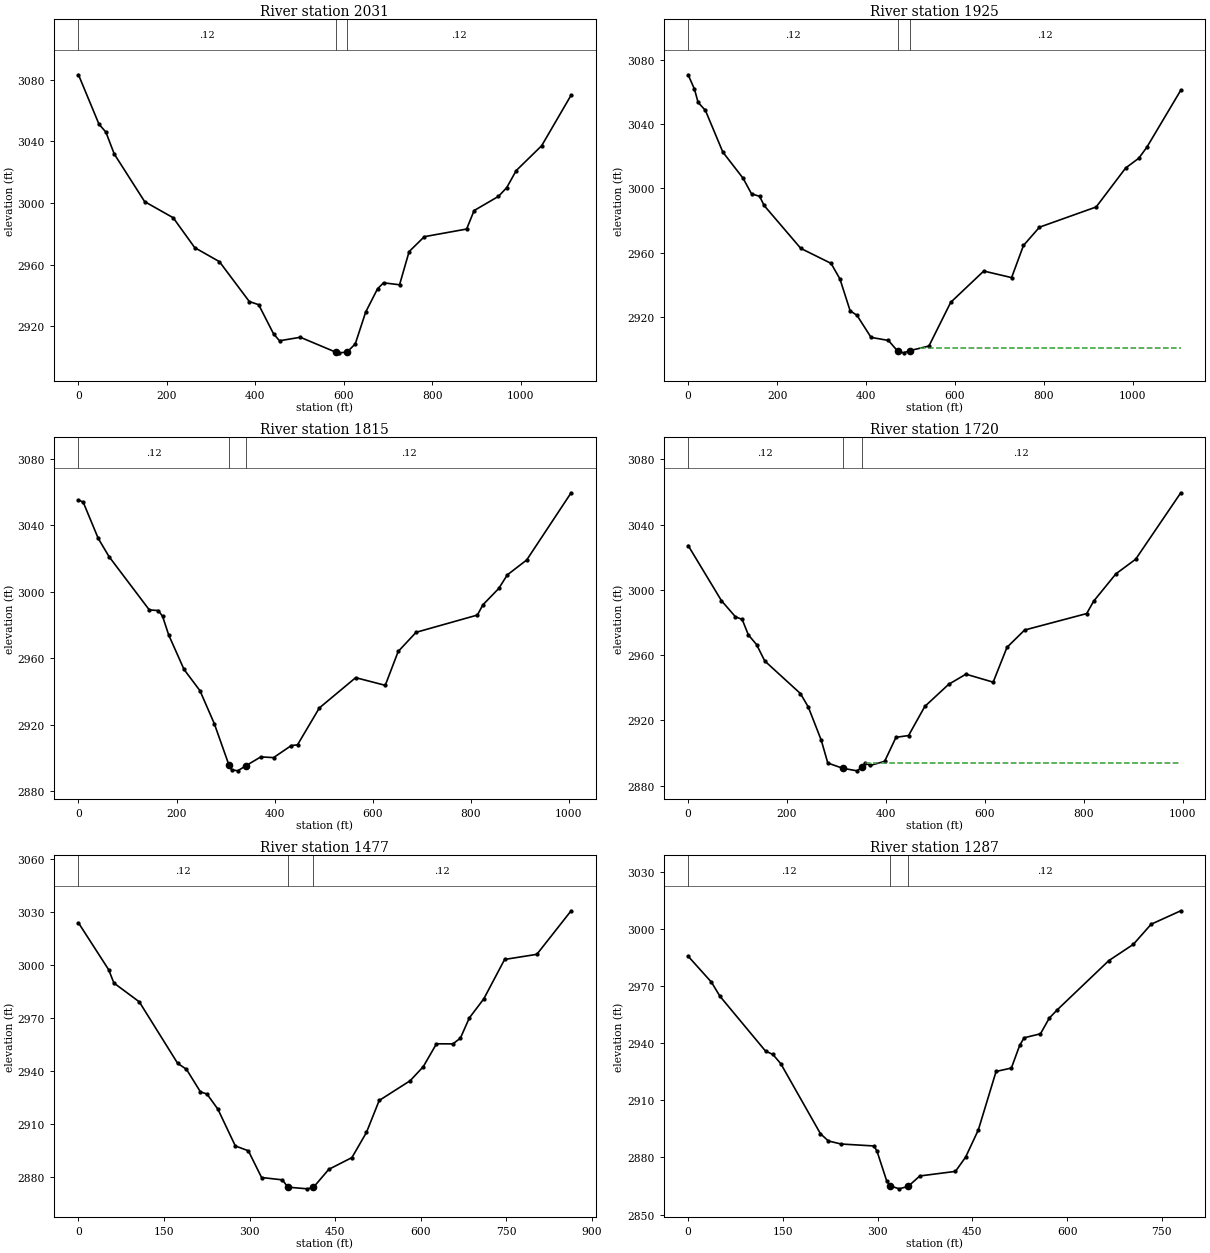
Type RM Length L Ch R = 1 ,2031    ,104.7,106.1,114.3
XS GIS Cut Line= 4
2123575.40736887  418656.65886352123829.31361887418357.179696828
2124143.11570218418288.1692801712124446.50111887418027.752613485
#Sta/Elev= 30
       0 3083.24    46.4 3051.14    61.9  3046.1    80.8 3031.89   149.6 3000.96
   214.2 2990.49   262.8 2971.11   318.6 2962.03   386.2 2936.17   407.4  2934.1
     441 2915.22   454.5  2910.7   501.5 2912.98   581.22903.384   588.8 2902.88
   607.2 2903.35   625.8 2908.69   649.3 2929.31   676.2 2944.47   689.8  2948.3
   725.9 2947.03   747.5 2968.55   781.9 2978.22   877.5 2983.18   894.5 2995.17
   949.5 3004.36   968.2 3010.03   989.6 3021.08  1047.2 3037.22  1113.8 3070.03
#Mann= 3 , 0 , 0
       0     .12       0   581.2     .04       0   607.2     .12       0
Bank Sta=581.2,607.2
XS Rating Curve= 0 ,0
Exp/Cntr(USF)=0,0
Exp/Cntr=0.3,0.1

Type RM Length L Ch R = 1 ,1925    ,131.2,109.9,98.6
XS GIS Cut Line= 4
2123663.69450576418708.3785089932123881.87401194418393.230333405
2124050.29327986418425.1279220272124464.96193195418058.943604644
#Sta/Elev= 30
       0 3070.68    14.2 3061.75    22.4 3053.47    38.8 3048.55      78 3022.59
   123.7 3006.26   142.5 2996.62   160.7 2995.08   170.8 2989.39   253.3 2962.69
   321.4 2953.36   341.4 2943.64   364.2 2923.94   379.8 2920.99   411.3 2907.34
   450.4 2905.41   471.4 2898.72   484.8 2897.71   498.2 2899.06   541.5 2901.93
   590.5 2929.13   664.8 2948.59   727.4  2944.5   754.1 2964.49   790.1 2975.87
   917.6 2988.45   983.9 3012.69  1013.3 3018.73  1031.6 3025.62  1107.9 3061.08
#Mann= 3 , 0 , 0
       0     .12       0   471.4     .04       0   498.2     .12       0
#XS Ineff= 2 , 0
                          521.86         2900.85
Permanent Ineff=
       F       F
Bank Sta=471.4,498.2
XS Rating Curve= 0 ,0
Exp/Cntr(USF)=0,0
Exp/Cntr=0.3,0.1

Type RM Length L Ch R = 1 ,1815    ,100,94.6,78.1
XS GIS Cut Line= 3
2123752.22566458418766.3518889182124050.90192541418427.369835112
2124466.45135674418063.000186176
#Sta/Elev= 30
       0 3055.29     9.6 3053.99    40.3 3032.16    62.2 3021.27   144.4 2989.17
   162.8 2988.78   171.5 2985.32   183.9 2974.13   215.2 2953.37   247.7 2940.58
   276.9 2920.79   307.1 2895.61   312.2 2893.07   324.6 2892.38     342 2895.55
   371.7 2900.77   397.8 2900.34   433.9 2907.58   446.6 2908.02   491.1  2930.2
   565.2 2948.42   625.5 2943.81   651.9 2964.19   688.4  2975.7   813.4 2986.08
   824.5  2992.2     857 3002.09   874.4 3010.24   913.9 3019.19  1004.5 3059.62
#Mann= 3 , 0 , 0
       0     .12       0   307.1     .04       0     342     .12       0
Bank Sta=307.1,342
XS Rating Curve= 0 ,0
Exp/Cntr(USF)=0,0
Exp/Cntr=0.3,0.1

Type RM Length L Ch R = 1 ,1720    ,234.3,243.4,253.6
XS GIS Cut Line= 4
2123904.83445215418825.9296968432124036.34486884418655.356780156
 2124046.7615355418436.6067801562124468.63653553418065.513030171
#Sta/Elev= 30
       0 3027.14    67.3 2993.34    95.4 2983.52   109.3 2981.81   121.7 2972.38
   138.3 2966.44   154.9 2956.37     227 2936.41     243 2928.12   269.2 2907.77
   282.4  2893.8   312.3 2890.62   341.5 2889.02   351.3 2891.24   357.9 2893.83
   367.8  2892.3   397.3 2894.82   420.3 2909.57   445.7 2910.65   478.6  2928.5
   526.7 2942.02   561.7 2948.27   616.8 2943.37   644.7  2964.7   680.4 2975.33
     806 2985.43   819.9 2992.97   865.1  3009.8   904.9 3018.71   996.2 3059.46
#Mann= 3 , 0 , 0
       0     .12       0   312.3     .04       0   351.3     .12       0
#XS Ineff= 2 , 0
                          358.57         2893.84
Permanent Ineff=
       F       F
Bank Sta=312.3,351.3
XS Rating Curve= 0 ,0
Exp/Cntr(USF)=0,0
Exp/Cntr=0.3,0.1

Type RM Length L Ch R = 1 ,1477    ,187.1,189.9,192.8
XS GIS Cut Line= 2
2124074.20647504418912.6408397812124519.84448244418172.795215832
#Sta/Elev= 30
       0 3024.01    52.9 2997.48    62.1 2989.93   106.6 2979.28   173.8 2944.47
   189.3 2941.06   213.8  2928.3   225.3 2927.04   244.4 2918.49     275 2897.65
   297.8  2894.9     321 2879.77   357.5 2878.43     367 2874.31   401.4 2873.35
   411.8 2874.16   438.8 2884.38   479.4 2891.06   504.9 2905.32   527.2  2923.4
   581.5  2934.6   604.4 2942.51   627.6 2955.51   656.3 2955.46   669.5 2958.67
   685.2 2970.14   710.7 2981.04   747.1 3003.29   803.6 3006.19   863.7 3030.86
#Mann= 3 , 0 , 0
       0     .12       0     367     .04       0   411.8     .12       0
Bank Sta=367,411.8
XS Rating Curve= 0 ,0
Exp/Cntr(USF)=0,0
Exp/Cntr=0.3,0.1

Type RM Length L Ch R = 1 ,1287    ,216.7,214.4,216.7
XS GIS Cut Line= 2
      2124221.46      418976.149     2124672.956        418340.2
#Sta/Elev= 30
       0 2985.67    36.9 2972.05    50.3 2964.68   122.5 2935.87   134.2 2934.09
   146.7 2929.22   209.5 2892.45     222 2888.67   242.1 2887.07   294.4 2886.04
     299 2883.27   314.5 2867.53   320.1 2865.05   334.3 2863.53   348.4 2864.87
   366.8 2870.29   423.2  2872.7   439.3  2880.2   459.4 2894.48   487.5 2925.17
   511.7 2926.96   524.9 2938.91   531.9 2942.85   557.8 2944.95   571.7 2953.17
   584.1 2957.45     666 2983.38   704.8 2991.91     733 3002.48   779.9 3009.54
#Mann= 3 , 0 , 0
       0     .12       0   320.1     .04       0   348.4     .12       0
Bank Sta=320.1,348.4
XS Rating Curve= 0 ,0
Exp/Cntr=0.3,0.1

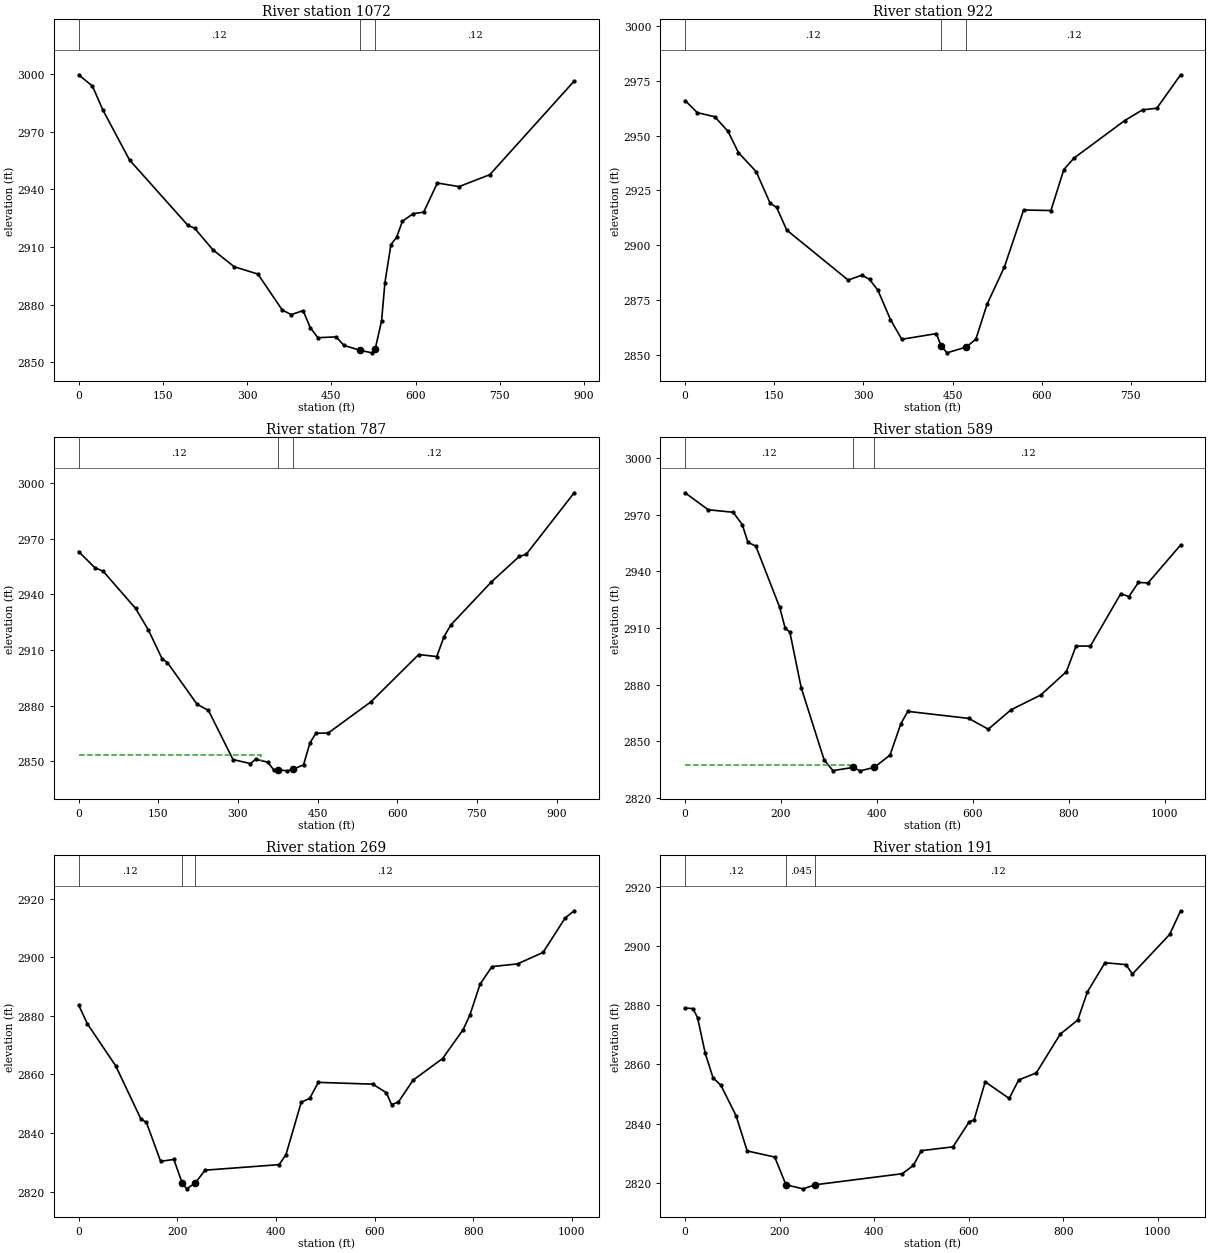
Type RM Length L Ch R = 1 ,1072    ,150.6,150.6,150.6
XS GIS Cut Line= 2
2124286.20902225419137.6231347832124844.33817716418454.023084584
#Sta/Elev= 30
       0 2999.84    24.6 2993.95    43.2 2981.46    90.6 2955.41   194.8 2921.22
   206.4 2919.86   238.8 2908.63     277 2899.71   319.3 2895.87   362.7 2877.11
   378.6 2874.73   399.8 2876.81   412.5 2867.91   426.1 2862.69   458.3 2863.11
   472.8 2858.63   501.4  2856.1   522.6 2854.79   528.2  2856.9   539.5 2871.44
   545.5 2891.47   556.2 2911.27   566.2 2915.04   576.6 2923.42   595.8  2927.4
   614.5 2928.17   638.8 2943.39   677.4 2941.51   732.2 2947.71   882.5 2996.56
#Mann= 3 , 0 , 0
       0     .12       0   501.4     .04       0   528.2     .12       0
Bank Sta=501.4,528.2
XS Rating Curve= 0 ,0
Exp/Cntr(USF)=0,0
Exp/Cntr=0.3,0.1

Type RM Length L Ch R = 1 ,922     ,134.6,134.6,134.6
XS GIS Cut Line= 4
2124376.32645497419201.3131449372124568.18219059 418974.96649055
2124738.48110199418817.6016736912124889.37887158418552.452735695
#Sta/Elev= 30
       0 2965.99    20.7 2960.45      50  2958.6    72.3 2951.91    89.7 2942.27
   119.6 2933.56   143.1 2919.17     154 2917.27     171 2906.92   274.4 2884.14
   297.6  2886.4   310.3 2884.44   324.4 2879.52   345.5 2866.12   364.6 2857.15
   422.7 2859.73   430.52854.267   440.6 2850.97   473.2 2853.64   489.2 2857.21
     508  2873.1   537.2 2890.12   569.5 2916.09   615.5 2915.84   637.2 2934.54
     654 2939.68   739.4 2956.83   769.6 2961.75   793.6 2962.49   833.7 2977.73
#Mann= 3 ,-1 , 0
       0     .12       0   430.5     .04       0   473.2     .12       0
Bank Sta=430.5,473.2
XS Rating Curve= 0 ,0
Exp/Cntr(USF)=0,0
Exp/Cntr=0.3,0.1

Type RM Length L Ch R = 1 ,787     ,197.6,198,190.7
XS GIS Cut Line= 3
     2124507.775      419284.488        2124940.      418764.166
     2124959.271      418508.135
#Sta/Elev= 30
       0 2962.96    30.5 2954.28    46.1  2952.4   107.3 2932.33   131.5 2920.68
   157.2 2905.23   167.2 2903.19   223.1 2880.72   244.5 2877.42   290.7 2850.96
   323.3  2848.8   333.3 2851.08   355.9 2849.57   367.7 2845.34     376 2845.46
   393.2 2844.88   403.6 2845.71   423.5 2848.12   435.7 2859.93   446.8 2865.13
   470.1 2865.27   550.9 2882.14   640.4 2907.51   674.5 2906.41   688.1 2917.17
   701.3 2923.58     777 2946.53   829.6 2960.32   842.8 2961.44   933.2 2994.63
#Mann= 3 , 0 , 0
       0     .12       0     376     .04       0   403.6     .12       0
#XS Ineff= 2 , 0
          343.48 2853.42
Permanent Ineff=
       F       F
Bank Sta=376,403.6
XS Rating Curve= 0 ,0
Exp/Cntr=0.3,0.1

Type RM Length L Ch R = 1 ,589     ,324.3,319.8,318
XS GIS Cut Line= 3
2124597.72296918419414.5244209392125052.01414178418942.926917954
2125121.23946332418570.840814682
#Sta/Elev= 30
       0 2981.62    48.2 2972.63   100.2 2971.29   119.2 2964.77   131.1 2955.37
   147.5 2953.37   197.2    2921   208.6 2909.99   218.5 2907.75   242.1 2878.41
     290 2840.09   308.3  2834.5  350.17 2836.15   365.1 2834.37  394.61 2836.23
   427.2 2842.67     450 2859.35   464.4 2865.86   591.6 2862.13   632.2 2856.42
   679.5 2866.68   741.7 2874.55   795.1  2886.9   815.1 2900.43   845.2 2900.48
   908.6 2928.27   925.3 2926.62   945.3 2934.14   965.3 2933.87  1033.3 2953.99
#Mann= 3 , 0 , 0
       0     .12       0  350.17     .04       0  394.61     .12       0
#XS Ineff= 2 , 0
           343.4 2837.34
Permanent Ineff=
       F       F
Bank Sta=350.17,394.61
XS Rating Curve= 0 ,0
Exp/Cntr(USF)=0,0
Exp/Cntr=0.5,0.3

Type RM Length L Ch R = 1 ,269     ,78,78,78
XS GIS Cut Line= 4
2124996.42812828419570.2193889682125031.63211527419431.711465346
2125060.82339035419271.141434483     2125278.622      418607.244
#Sta/Elev= 30
       0 2883.67    17.8 2877.26    75.3 2862.88   126.1 2844.83   137.4  2843.6
   166.3  2830.3     193 2830.99   209.7 2823.05     219 2820.93   236.4 2822.91
   256.4  2827.3   406.5 2829.19   420.4 2832.59   451.4  2850.5   468.7 2851.85
     486 2857.28   596.4 2856.67   624.1 2853.74   634.4 2849.71   648.2 2850.53
   678.2 2858.05     738 2865.41   779.5 2875.24   793.3 2880.25     814 2890.81
   838.1  2896.8   889.9 2897.72   941.7 2901.64   986.6 2913.42  1004.8 2915.86
#Mann= 3 ,-1 , 0
       0     .12       0   209.7    .045       0   236.4     .12       0
Bank Sta=209.7,236.4
XS Rating Curve= 0 ,0
Exp/Cntr=0.5,0.3

Type RM Length L Ch R = 1 ,191     ,191,191,191
XS GIS Cut Line= 6
2125099.87583895419628.5232494152125107.00256559419453.409394947
2125113.11118842419315.965381266 2125149.7629254419201.937755101
2125254.62761732418773.3160531772125303.49659996418605.328925344
#Sta/Elev= 30
       0 2879.06    16.5 2878.89    26.3 2875.86    42.7 2863.71    59.2 2855.44
    75.6 2852.98   107.8 2842.68   131.4 2830.73   189.7 2828.66   213.5 2819.28
   249.7 2817.91   275.9  2819.3   459.7 2823.03   483.2 2825.85   500.1 2830.82
     567 2832.12   601.5 2840.64   611.5 2841.19   635.2 2854.11   685.9 2848.49
   706.2 2854.75   743.3 2857.12     794 2870.24   831.1 2875.02   851.4 2884.51
   888.7  2894.4     933 2893.75   946.8 2890.58  1025.6 2903.971048.826 2911.97
#Mann= 3 , 0 , 0
       0     .12       0   213.5    .045       0   275.9     .12       0
Bank Sta=213.5,275.9
XS Rating Curve= 0 ,0
Exp/Cntr(USF)=0,0
Exp/Cntr=0.3,0.1
LCMann Table=0

Chan Stop Cuts=-1
Use User Specified Reach Order=0
Composite Channel Slope=5